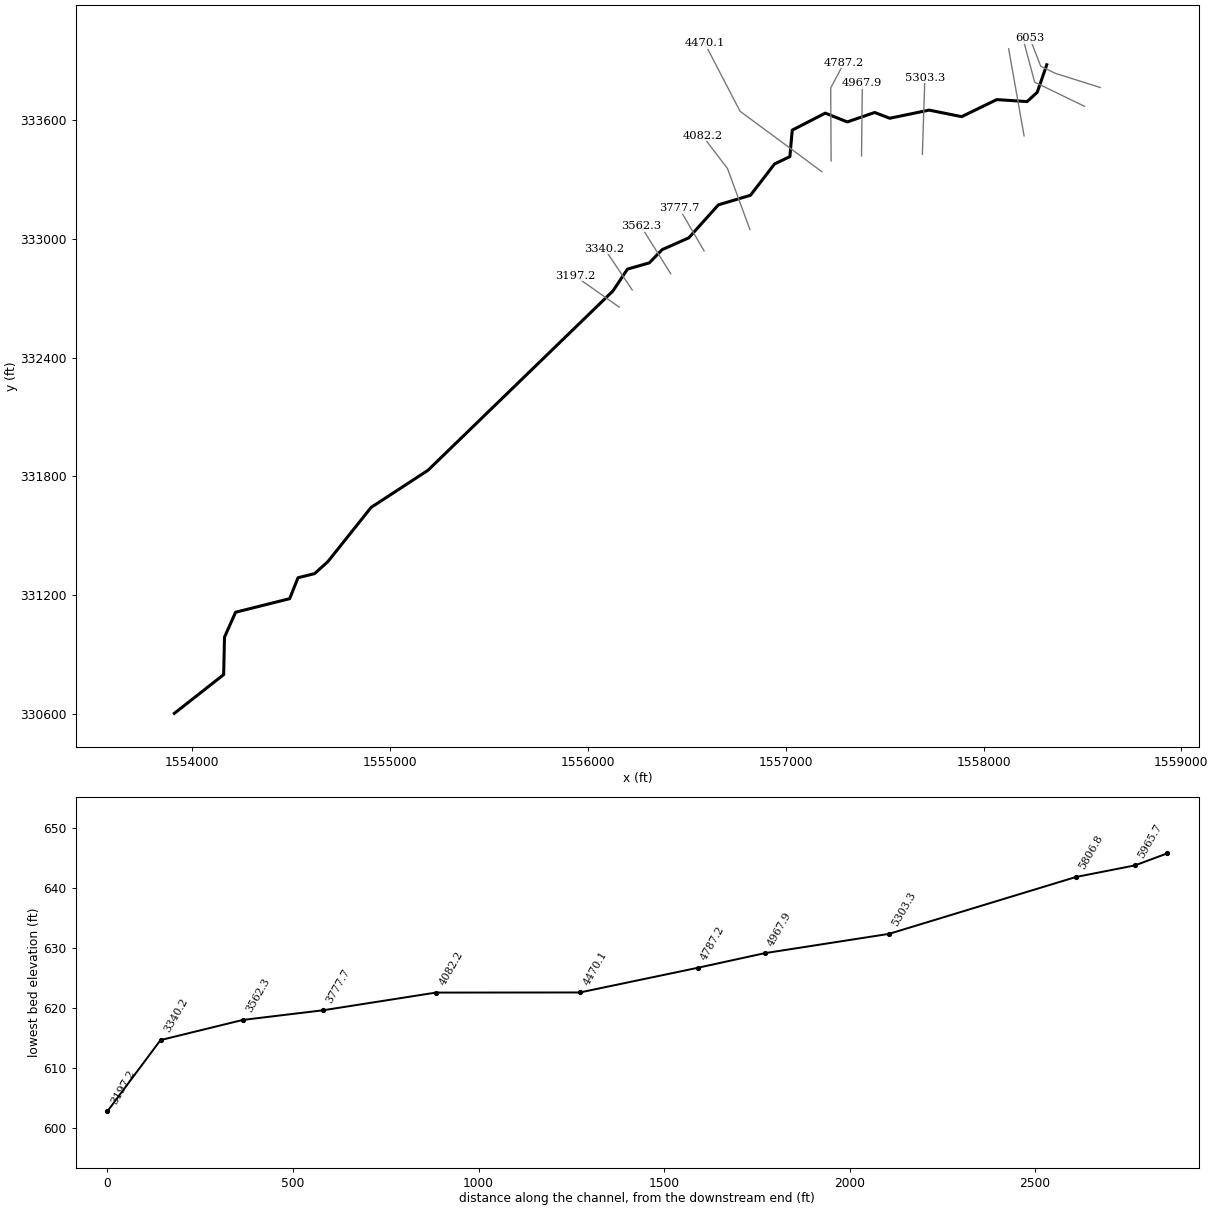
--- SILVERCR.prj (project) ---

Proj Title=SILVERCR
Current Plan=p01
Default Exp/Contr=0,0
English Units
Geom File=g01
Flow File=f01
Plan File=p01
BEGIN DESCRIPTION:
END DESCRIPTION:
DSS Export Rating Curves= 0
DSS Export Rating Curve Sorted= 0
DSS Export Volume Flow Curves= 0
DXF OffsetX= 0
DXF OffsetY= 0
DXF ScaleX= 0
DXF ScaleY= 0

--- SILVERCR.p01 (plan) ---

Plan Title=Floodplain
Program Version=4.00
Geom File=g01
Flow File=f01
K Sum by GR=0
Std Step Tol=0.01
Critical Tol=0.01
Num of Std Step Trials=20
Max Error Tol=0.3
Flow Tol Ratio=0.001
Split Flow NTrial=30
Split Flow Tol=0.02
Split Flow Ratio=0.02
Log Output Level=0
Friction Slope Method=1
Unsteady Friction Slope Method=2
Unsteady Bridges Friction Slope Method=1
Global Log Level=0
CheckData=False
Run HTab=0
Run UNet=0
Run PostProcess=0
UNET Theta=0
UNET Theta Warmup=0
UNET ZTol=0
UNET ZSATol=0
UNET MxIter=0
UNET MaxInSteps=0
UNET DtIC=0
UNET DtMin=0
UNET MaxCRTS=0
UNET WFStab=0
UNET SFStab=0
UNET WFX=0
UNET SFX=0
UNET DSS MLevel=0
UNET DZMax Abort=0
UNET Convert EG Bridges=0
UNET Use Existing IB Tables=0
UNET Froude Limit=0
UNET Froude Power=0
Write IC File=0
Echo Input=False
Echo Output=False
Write Detailed=0

--- SILVERCR.f01 (steady flow) ---

Flow Title=NFF Regression Equation
Program Version=4.00
Number of Profiles= 1
Profile Names=P100yr
River Rch & RM=SILVERCR,Main            ,6053
373.5043
River Rch & RM=SILVERCR,Main            ,4787.2
391.7093
River Rch & RM=SILVERCR,Main            ,4470.1
521.7812
Boundary for River Rch & Prof#=SILVERCR,Main            , 1
Up Type= 0
Dn Type= 3
Dn Slope=0.015
DSS Import GetInterval= 0
DSS Import GetPeak= 0
DSS Import FillOption= 0

--- SILVERCR.g01 (geometry) ---

Geom Title=Geometry
Program Version=4.00

River Reach=SILVERCR        ,Main
Reach XY= 30
     1558319.471      333880.675      1558271.07        333741.3
     1558219.904      333694.649      1558066.87      333704.751
     1557889.058      333618.461     1557724.753      333651.581
      1557525.51      333610.382      1557449.39      333639.635
      1557311.04      333591.823     1557199.822      333636.328
     1557032.803      333550.317     1557020.762      333416.388
     1556943.297       333379.29     1556821.577      333221.031
      1556659.27      333172.554     1556509.553      333005.692
     1556374.594      332945.928     1556310.491      332879.334
     1556199.667       332847.71     1556126.325      332737.303
     1555190.914      331830.445     1554903.526      331642.887
     1554684.936      331368.676     1554617.676      331308.057
     1554534.152      331287.433      1554491.78      331181.496
     1554218.366       331112.96     1554162.329      330986.845
     1554158.235      330797.593     1553908.771      330601.644

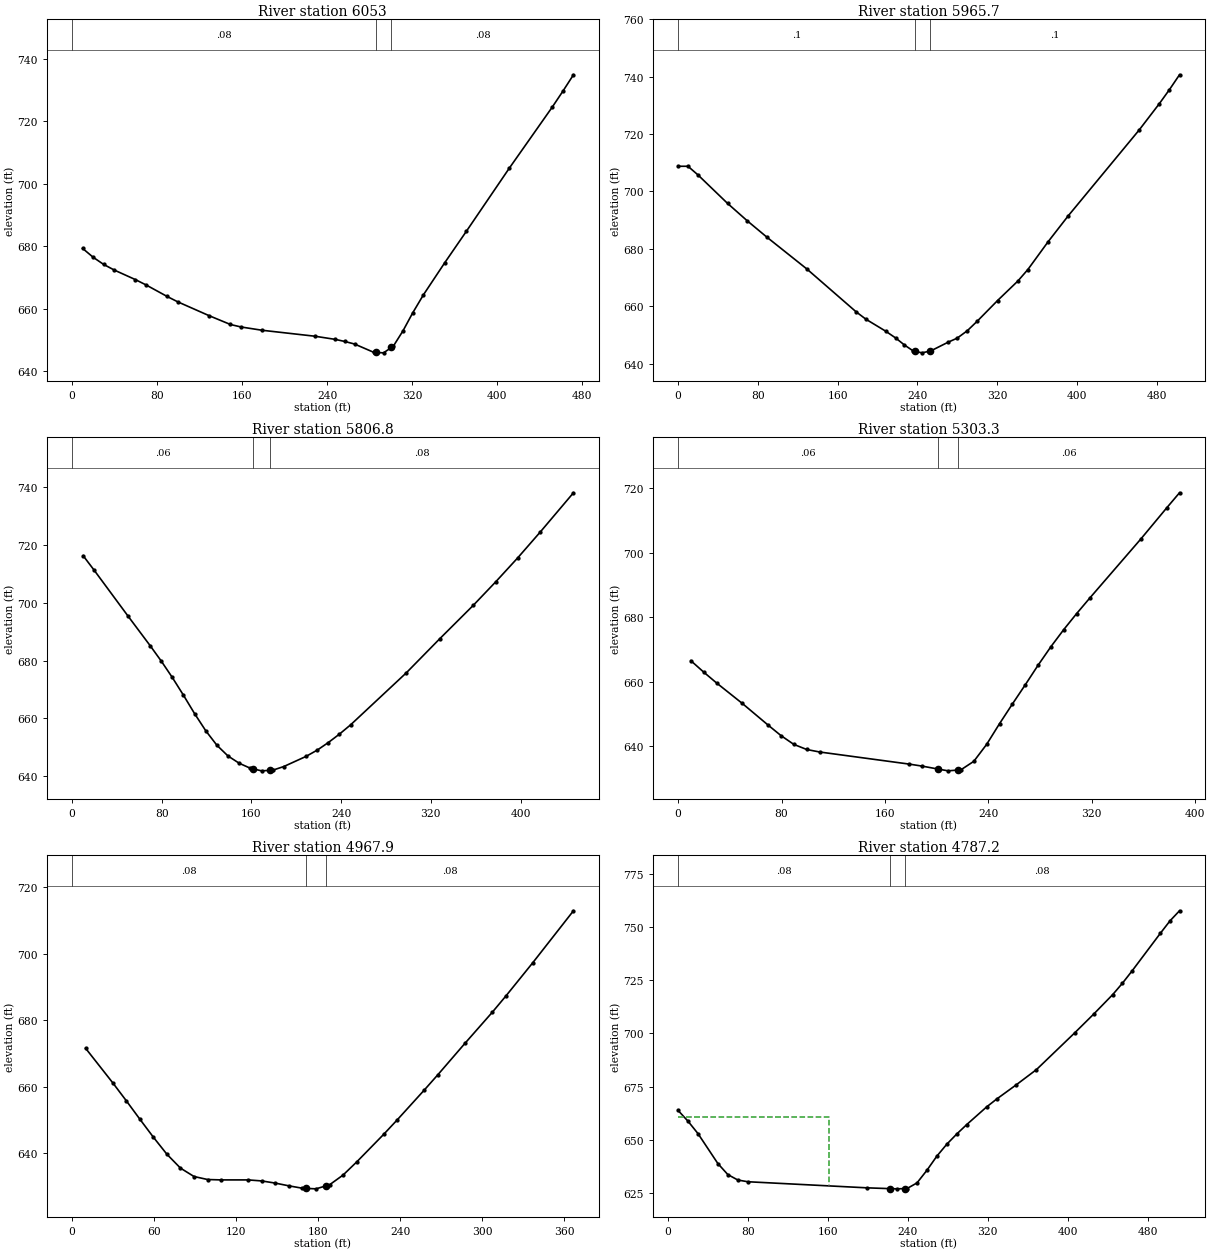
Type RM Length L Ch R = 1 ,6053    ,87.2,87.2,87.3
XS GIS Cut Line= 4
     1558590.396      333765.788     1558362.824      333837.431
     1558289.073      333873.253     1558234.287      334014.432
#Sta/Elev= 30
     9.9  679.31    19.9  676.45    29.8  674.15    39.8  672.35    59.6   669.3
    69.6   667.6    89.5  663.89    99.4  662.18   129.2   657.7   149.1   654.9
   159.1   654.1   178.9  653.05   228.6  651.14   247.7  650.13   256.8  649.45
   265.9  648.64   284.1  645.96   285.7  645.93   293.2  645.81   300.7  647.54
   302.4  647.93   311.5  652.85   320.6  658.58   330.7  664.38   350.9  674.74
   371.1  684.74   411.4  704.93   451.8   724.5   461.9  729.64     472  734.98
#Mann= 3 , 0 , 0
       0     .08       0   285.7    .045       0   300.7     .08       0
Bank Sta=285.7,300.7
XS Rating Curve= 0 ,0
Exp/Cntr=0.3,0.1

Type RM Length L Ch R = 1 ,5965.7  ,180.1,159,137.8
XS GIS Cut Line= 4
     1558510.347      333670.776     1558313.873      333765.844
     1558258.416       333792.78     1558200.583      334008.268
#Sta/Elev= 30
       0  708.78     9.9  708.78    19.8  705.81    49.6  695.86    69.4  689.78
    89.3  684.03     129  673.06   178.6  658.09   188.5   655.5   208.3  651.34
   218.3  648.97   227.1  646.53   235.9  644.46   237.2  644.36   244.7  643.81
   252.2  644.39   253.5  644.49   271.1  647.55   279.9  648.91   290.1   651.5
   300.2  654.87   320.5  662.03   340.8   668.8   350.9  672.83   371.2  682.51
   391.5  691.58   462.5   721.4   482.7  730.55   492.9  735.47     503  740.64
#Mann= 3 , 0 , 0
       0      .1       0   237.2    .045       0   252.2      .1       0
Bank Sta=237.2,252.2
XS Rating Curve= 0 ,0
Exp/Cntr=0.3,0.1

Type RM Length L Ch R = 1 ,5806.8  ,508.5,503.5,498.5
XS GIS Cut Line= 2
     1558204.787      333521.359     1558126.823      333961.753
#Sta/Elev= 30
     9.9  716.25    19.9  711.14    49.7  695.49    69.6  685.18    79.5  679.86
    89.4  674.17    99.4     668   109.3  661.65   119.3  655.71   129.2  650.72
   139.1  647.01   149.1   644.5     159  642.78   161.5  642.56     169  641.88
   176.5  642.04   178.9  642.09   188.8  643.36   208.7  646.87   218.7  649.05
   228.6  651.67   238.5  654.58   248.5   657.8   298.2  675.79     328  687.56
   357.8  699.07   377.7  707.15   397.5  715.51   417.4  724.35   447.2     738
#Mann= 3 , 0 , 0
       0     .06       0   161.5    .045       0   176.5     .08       0
Bank Sta=161.5,176.5
XS Rating Curve= 0 ,0
Exp/Cntr=0.3,0.1

Type RM Length L Ch R = 1 ,5303.3  ,334.9,335.4,335.9
XS GIS Cut Line= 2
     1557690.643      333428.644     1557703.286       333816.36
#Sta/Elev= 28
     9.9  666.57    19.9     663    29.8  659.66    49.7  653.31    69.6  646.61
    79.6  643.34    89.5  640.62    99.5  639.03   109.4  638.26     179  634.49
     189  633.86   201.4  632.94   208.9  632.41   216.4  632.65   218.8  632.73
   228.8  635.37   238.7  640.62   248.7  647.06   258.6  653.13   268.6  659.11
   278.5  665.18   288.5  670.97   298.4  676.25   308.3  681.18   318.3  685.92
   358.1  704.38     378  713.98   387.9  718.66
#Mann= 3 , 0 , 0
       0     .06       0   201.4    .045       0   216.4     .06       0
Bank Sta=201.4,216.4
XS Rating Curve= 0 ,0
Exp/Cntr=0.3,0.1

Type RM Length L Ch R = 1 ,4967.9  ,180.4,180.7,180.8
XS GIS Cut Line= 2
     1557382.999      333420.216     1557387.214       333786.86
#Sta/Elev= 30
     9.9  671.53    29.7  661.16    39.6  655.76    49.5  650.22    59.5  644.73
    69.4   639.6    79.3  635.43    89.2   632.9    99.1     632     109  631.88
   128.8  631.88   138.7  631.57   148.6  630.92   158.6  630.09   168.5  629.37
   170.9  629.33   178.4  629.19   185.9  630.11   188.3   630.4   198.2  633.34
   208.1  637.26   227.9   645.6   237.8  649.96   257.7  658.99   267.6  663.59
   287.4  673.04   307.2  682.31   317.1  687.18   336.9  697.27   366.7  712.94
#Mann= 3 , 0 , 0
       0     .08       0   170.9    .045       0   185.9     .08       0
Bank Sta=170.9,185.9
XS Rating Curve= 0 ,0
Exp/Cntr=0.3,0.1

Type RM Length L Ch R = 1 ,4787.2  ,297.1,317.1,331.8
XS GIS Cut Line= 3
     1557229.177       333394.93      1557227.07      333763.681
     1557294.499       333890.11
#Sta/Elev= 30
      10  663.72    19.9  658.66    29.9   652.8    49.8  638.69    59.8  633.47
    69.8  630.91    79.7   630.1   199.3  627.22   221.7  626.85   229.2  626.75
   236.7  626.86   239.2  626.89   249.2  629.55   259.1  635.49   269.1  642.19
   279.1  647.83     289  652.61     299  657.06   318.9  665.38   328.9  669.07
   348.8  675.88   368.8  682.98     407  700.26   426.1  709.15   445.2  718.38
   454.7  723.61   464.3  729.37   492.9  747.29   502.5  753.12     512  757.86
#Mann= 3 , 0 , 0
      10     .08       0   221.7    .045       0   236.7     .08       0
#XS Ineff= 2 , 0
          161.07  660.81
Permanent Ineff=
       F       F
Bank Sta=221.7,236.7
XS Rating Curve= 0 ,0
Exp/Cntr=0.3,0.1

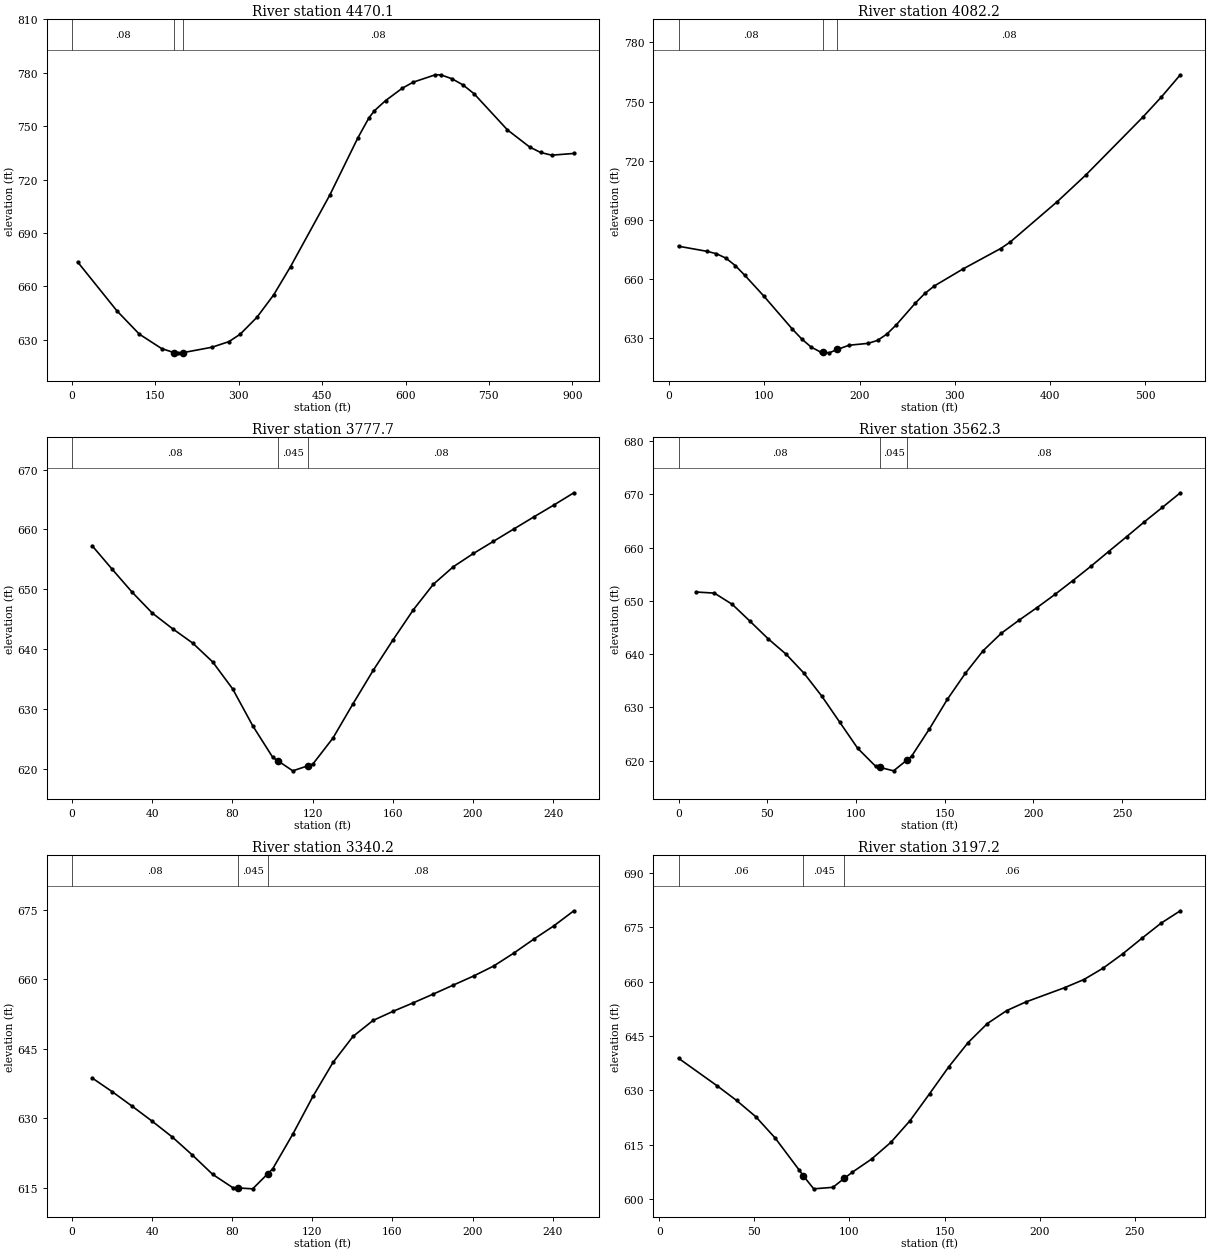
Type RM Length L Ch R = 1 ,4470.1  ,399.7,387.9,389.1
XS GIS Cut Line= 3
     1557182.293      333340.408     1556768.765      333645.944
     1556589.658       333990.99
#Sta/Elev= 30
    10.1  673.68    80.7  646.25     121  633.16   161.3  625.02     184  622.73
   191.5  622.65     199  622.72     252  625.82   282.3  628.96   302.4  633.09
   332.7  642.65   362.9  655.28   393.2  671.15   463.7  711.27   514.2  743.42
   534.1  754.66   544.1   758.7     564  764.36   593.9  771.28   613.8  774.74
   653.7  778.89   663.7  778.84   683.6  776.65   703.6  773.16   723.5  768.19
   783.3  747.95   823.2  738.34   843.1  735.24     863  733.71   902.9  734.69
#Mann= 3 , 0 , 0
       0     .08       0     184    .045       0     199     .08       0
Bank Sta=184,199
XS Rating Curve= 0 ,0
Exp/Cntr=0.3,0.1

Type RM Length L Ch R = 1 ,4082.2  ,300.9,304.6,308.4
XS GIS Cut Line= 3
     1556818.627      333048.004     1556705.367      333356.175
     1556578.939      333522.113
#Sta/Elev= 30
     9.9  676.67    39.8  674.08    49.7  672.87    59.7  670.62    69.6  666.82
    79.6  661.88    99.5  651.39   129.3  634.73   139.3  629.66   149.2  625.52
   159.2  623.02   161.6  623.01  168.13  622.63   176.6  624.33     189  626.49
   208.9  627.43   218.9  628.93   228.8  632.17   238.8  636.93   258.7  647.89
   268.6  652.73   278.6  656.55   308.4  665.07   348.2   675.5   358.1  678.74
   407.8  699.33   437.6  712.75   497.2  741.94   517.1  752.37   536.9  763.57
#Mann= 3 , 0 , 0
     9.9     .08       0   161.6    .045       0   176.6     .08       0
Bank Sta=161.6,176.6
XS Rating Curve= 0 ,0
Exp/Cntr=0.3,0.1

Type RM Length L Ch R = 1 ,3777.7  ,214.2,215.4,216.4
XS GIS Cut Line= 2
     1556587.024      332940.049     1556460.595      333156.032
#Sta/Elev= 27
      10  657.29      20  653.36      30  649.51      40  646.04    50.1  643.43
    60.1  641.04    70.1  637.89    80.1  633.37    90.1  627.22   100.1  621.93
   102.6  621.37   110.1  619.68   117.6  620.52   120.1  620.81   130.1  625.14
   140.1  630.86   150.2  636.46   160.2  641.61   170.2  646.57   180.2  650.84
   190.2  653.78   200.2  655.99   210.2  658.02   220.2  660.05   230.2  662.07
   240.3  664.08   250.3  666.13
#Mann= 3 , 0 , 0
       0     .08       0   102.6    .045       0   117.6     .08       0
Bank Sta=102.6,117.6
XS Rating Curve= 0 ,0
Exp/Cntr=0.3,0.1

Type RM Length L Ch R = 1 ,3562.3  ,221.7,222.1,222.5
XS GIS Cut Line= 2
     1556418.452      332824.156     1556268.318      333063.844
#Sta/Elev= 30
    10.1  651.66    20.2  651.46    30.3  649.34    40.4  646.14    50.5  642.88
    60.6  639.99    70.7  636.42    80.8  632.08    90.9  627.19     101   622.3
   111.1  618.93   113.7  618.71   121.2  618.08   128.7   620.1   131.3   620.8
   141.4  625.96   151.5  631.51   161.6  636.38   171.7  640.65   181.8  643.89
   191.9  646.37     202  648.73   212.1   651.2   222.2   653.8   232.3  656.47
   242.4  659.27   252.5  662.04   262.6  664.86   272.7  667.56   282.8   670.3
#Mann= 3 , 0 , 0
       0     .08       0   113.7    .045       0   128.7     .08       0
Bank Sta=113.7,128.7
XS Rating Curve= 0 ,0
Exp/Cntr=0.3,0.1

Type RM Length L Ch R = 1 ,3340.2  ,134.6,143,151.4
XS GIS Cut Line= 2
     1556223.541      332742.504     1556083.942      332950.585
#Sta/Elev= 27
      10  638.66      20  635.71    30.1  632.53    40.1  629.29    50.1  625.89
    60.1  622.01    70.2  617.85    80.2  614.99    82.7  614.92    90.2  614.72
    97.7  617.96   100.2  619.04   110.3  626.58   120.3  634.69   130.3     642
   140.3  647.62   150.3  651.07   160.4  653.06   170.4  654.88   180.4  656.77
   190.4  658.71   200.5  660.66   210.5  662.81   220.5  665.58   230.5   668.6
   240.5  671.46   250.6  674.75
#Mann= 3 , 0 , 0
       0     .08       0    82.7    .045       0    97.7     .08       0
Bank Sta=82.7,97.7
XS Rating Curve= 0 ,0
Exp/Cntr=0.3,0.1

Type RM Length L Ch R = 1 ,3197.2  ,3203,3197.2,3191.4
XS GIS Cut Line= 2
     1556157.692      332655.584     1555933.808       332813.62
#Sta/Elev= 27
    10.1  638.89    30.4  631.29    40.6  627.26    50.7  622.78    60.9   616.9
    73.7  607.95    75.7  606.48    81.2  602.87    91.3  603.29   97.33  605.79
   101.5  607.46   111.6  611.07   121.8  615.71   131.9  621.71   142.1  629.09
   152.2  636.52   162.4  643.22   172.5  648.46   182.7  652.04   192.8  654.43
   213.1  658.35   223.3  660.61   233.4  663.75   243.6  667.65   253.7  671.95
   263.9  676.16     274  679.57
#Mann= 3 , 0 , 0
    10.1     .06       0    75.7    .045       0   97.33     .06       0
Bank Sta=75.7,97.33
XS Rating Curve= 0 ,0
Exp/Cntr=0.3,0.1

Chan Stop Cuts=-1
Use User Specified Reach Order=0